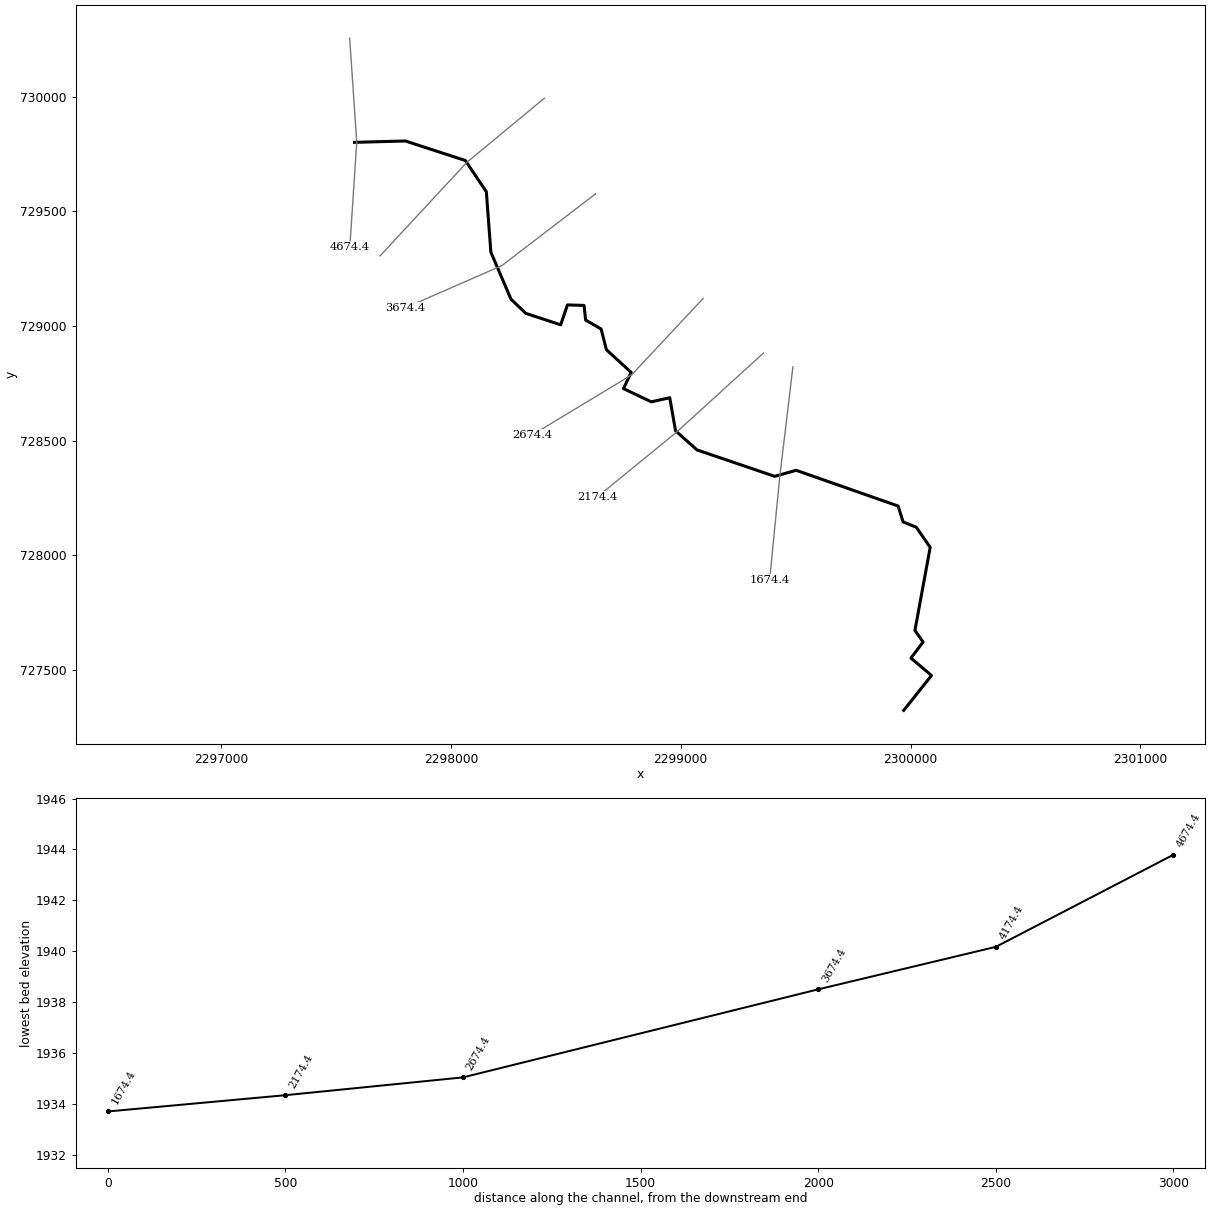
--- HORSERN.prj (project) ---

Proj Title=HORSERN
Current Plan=p01
Geom File=g01
Flow File=f01
Plan File=p01
DSS Export Rating Curves=0
DSS Export Rating Curve Sorted=0
DSS Export Volume Flow Curves=0
DXF OffsetX=0
DXF OffsetY=0
DXF ScaleX=0
DXF ScaleY=0

--- HORSERN.p01 (plan) ---

Plan Title=Floodplain
Program Version=4.00
Geom File=g01
Flow File=f01
K Sum by GR=0
Std Step Tol=0.01
Critical Tol=0.01
Num of Std Step Trials=20
Max Error Tol=0.3
Flow Tol Ratio=0.001
Split Flow NTrial=30
Split Flow Tol=0.02
Split Flow Ratio=0.02
Log Output Level=0
Friction Slope Method=1
Unsteady Friction Slope Method=2
Unsteady Bridges Friction Slope Method=1
Global Log Level=0
CheckData=False
Run HTab=0
Run UNet=0
Run PostProcess=0
UNET Theta=0
UNET Theta Warmup=0
UNET ZTol=0
UNET ZSATol=0
UNET MxIter=0
UNET MaxInSteps=0
UNET DtIC=0
UNET DtMin=0
UNET MaxCRTS=0
UNET WFStab=0
UNET SFStab=0
UNET WFX=0
UNET SFX=0
UNET DSS MLevel=0
UNET DZMax Abort=0
UNET Convert EG Bridges=0
UNET Use Existing IB Tables=0
UNET Froude Limit=0
UNET Froude Power=0
Write IC File=0
Echo Input=False
Echo Output=False
Write Detailed=0

--- HORSERN.f01 (steady flow) ---

Flow Title=Flow
Program Version=4.00
Number of Profiles=1
Profile Names=P100yr
River Rch & RM=HORSERN,Main      ,4674.4
304.7762
River Rch & RM=HORSERN,Main      ,3674.4
319.6633
River Rch & RM=HORSERN,Main      ,3674.4
318.5106
River Rch & RM=HORSERN,Main      ,2674.4
339.8156
River Rch & RM=HORSERN,Main      ,2674.4
337.7129
River Rch & RM=HORSERN,Main      ,2674.4
323.4835
River Rch & RM=HORSERN,Main      ,2174.4
346.6516
River Rch & RM=HORSERN,Main      ,2174.4
344.4003
River Rch & RM=HORSERN,Main      ,1674.4
357.2588
River Rch & RM=HORSERN,Main      ,1674.4
355.0771
Boundary for River Rch & Prof#=HORSERN,Main      ,1
Up Type=0
Dn Type=3
Dn Slope=0.002042

--- HORSERN.g01 (geometry) ---

Geom Title=Geometry
Program Version=4.00

River Reach=HORSERN     ,Main
Reach XY= 30
     2297579.967      729801.367     2297801.495      729807.270
     2298062.606      729722.200     2298153.926      729586.089
     2298173.718      729322.201     2298261.217      729117.339
     2298325.801      729055.534     2298477.537      729005.534
     2298506.935      729092.339     2298579.157      729090.256
     2298586.102      729026.367     2298653.463      728987.478
     2298676.380      728897.200     2298784.400      728797.964
     2298750.807      728727.391     2298871.889      728669.785
     2298952.184      728687.580     2298977.358      728543.483
     2299070.674      728460.150     2299409.216      728344.698
     2299502.098      728371.174     2299946.108      728215.358
     2299967.809      728145.914     2300024.985      728123.055
     2300085.749      728035.381     2300019.300      727672.925
     2300054.716      727622.230     2300001.939      727552.091
     2300091.522      727476.397     2299970.593      727324.284

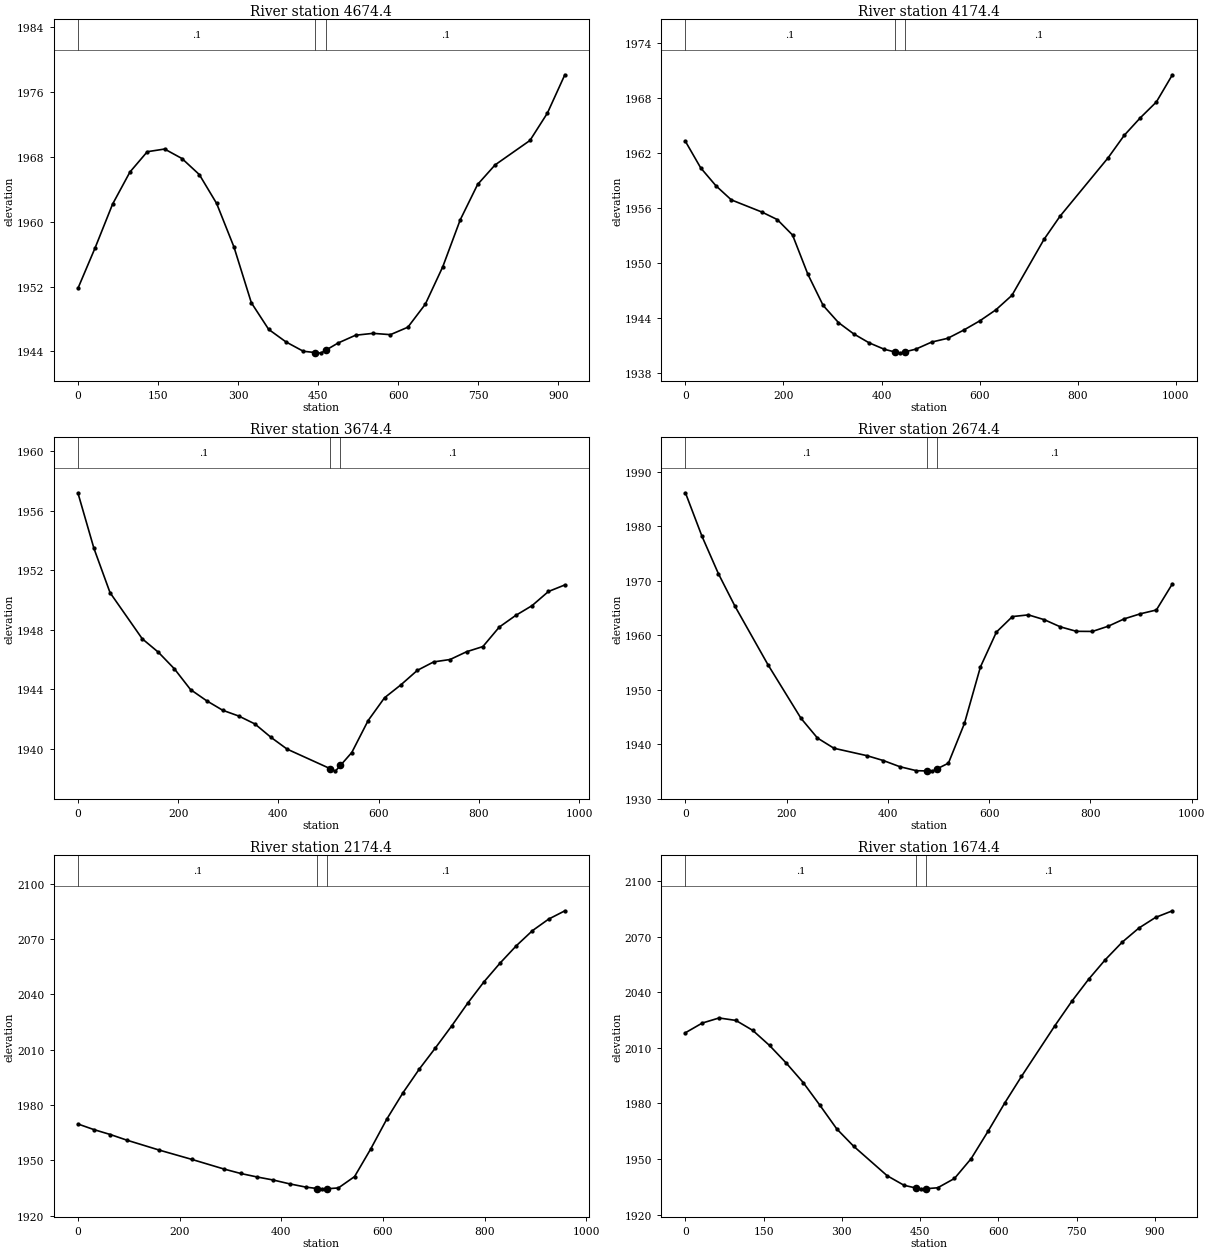
Type RM Length L Ch R = 1 ,4674.4,523.5,500,482.2
XS GIS Cut Line= 3
     2297559.173      730255.572     2297589.963      729801.666
     2297559.892      729345.190
#Sta/Elev= 30
       0 1951.77    32.5 1956.82    65.0 1962.18    97.5 1966.14   130.0 1968.65
   162.5 1968.98   195.0 1967.81   227.5 1965.83   260.0 1962.26   292.5 1956.88
   325.0 1950.01   357.5 1946.72   390.0 1945.17   422.4 1944.02     445 1943.86
   455.0 1943.79     465 1944.17   487.6 1945.04   520.3 1946.00   553.0 1946.23
   585.6 1946.07   618.3 1946.99   651.0 1949.83   683.7 1954.45   716.4 1960.24
   749.0 1964.61   781.7 1967.02   847.1 1970.04   879.7 1973.41   912.4 1978.14
#Mann= 3 , 0 , 0
       0     0.1       0     445   0.045       0     465     0.1       0
Bank Sta=445,465
Exp/Cntr=0.3,0.1

Type RM Length L Ch R = 1 ,4174.4,499.5,500,488.7
XS GIS Cut Line= 3
     2298406.076      729993.324     2298069.644      729714.523
     2297691.651      729306.279
#Sta/Elev= 30
       0 1963.30    31.2 1960.40    62.4 1958.44    93.6 1956.91   156.0 1955.58
   187.3 1954.76   218.5 1953.07   249.7 1948.79   280.9 1945.38   312.1 1943.51
   343.3 1942.27   374.5 1941.30   405.7 1940.59   426.9 1940.30   436.9 1940.17
   446.9 1940.30   469.7 1940.60   502.4 1941.38   535.1 1941.79   567.8 1942.69
   600.6 1943.70   633.3 1944.90   666.0 1946.48   731.5 1952.60   764.2 1955.13
   862.4 1961.52   895.1 1963.96   927.8 1965.87   960.6 1967.60   993.3 1970.57
#Mann= 3 , 0 , 0
       0     0.1       0   426.9   0.045       0   446.9     0.1       0
Bank Sta=426.9,446.9
Exp/Cntr=0.3,0.1

Type RM Length L Ch R = 1 ,3674.4,980.8,1000,1056.3
XS GIS Cut Line= 3
     2298629.094      729576.632     2298221.472      729263.751
     2297802.031      729079.929
#Sta/Elev= 30
       0 1957.20    32.1 1953.46    64.2 1950.49   128.5 1947.39   160.6 1946.49
   192.7 1945.37   224.8 1943.98   256.9 1943.23   289.0 1942.59   321.2 1942.20
   353.3 1941.67   385.4 1940.77   417.5 1939.98   503.9 1938.66   513.9 1938.50
   523.9 1938.88   546.6 1939.75   579.3 1941.90   612.0 1943.43   644.7 1944.30
   677.4 1945.27   710.1 1945.84   742.8 1946.00   775.6 1946.52   808.3 1946.87
   841.0 1948.18   873.7 1948.96   906.4 1949.62   939.1 1950.57   971.8 1951.01
#Mann= 3 , 0 , 0
       0     0.1       0   503.9   0.045       0   523.9     0.1       0
Bank Sta=503.9,523.9
Exp/Cntr=0.3,0.1

Type RM Length L Ch R = 1 ,2674.4,468,500,415.7
XS GIS Cut Line= 3
     2299097.533      729120.569     2298786.040      728787.100
     2298353.499      728525.326
#Sta/Elev= 30
       0 1986.16    32.6 1978.20    65.2 1971.29    97.8 1965.34   163.0 1954.59
   228.2 1944.75   260.8 1941.12   293.4 1939.24   358.5 1937.88   391.1 1936.98
   423.7 1935.85   456.3 1935.12   477.9 1935.07   487.9 1935.04   497.9 1935.50
   519.5 1936.50   551.1 1943.79   582.7 1954.17   614.3 1960.58   645.9 1963.43
   677.5 1963.74   709.1 1962.85   740.7 1961.54   772.3 1960.72   803.9 1960.70
   835.5 1961.67   867.1 1963.02   898.7 1963.94   930.3 1964.64   961.9 1969.44
#Mann= 3 , 0 , 0
       0     0.1       0   477.9   0.045       0   497.9     0.1       0
Bank Sta=477.9,497.9
Exp/Cntr=0.3,0.1

Type RM Length L Ch R = 1 ,2174.4,489,500,519.7
XS GIS Cut Line= 3
     2299360.331      728882.777     2298981.807      728537.477
     2298637.150      728255.280
#Sta/Elev= 30
       0 1969.70    32.0 1966.60    64.0 1963.96    96.1 1960.94   160.1 1955.52
   224.2 1950.47   288.2 1945.18   320.2 1942.84   352.2 1940.95   384.3 1939.28
   416.3 1937.21   448.3 1935.44   470.3 1934.68   480.3 1934.34   490.3 1934.54
   512.4 1934.99   544.2 1941.14   576.0 1956.14   607.8 1972.43   639.6 1986.70
   671.4 1999.44   703.3 2011.00   735.1 2022.85   766.9 2035.31   798.7 2046.82
   830.5 2057.04   862.4 2066.43   894.2 2074.64   926.0 2080.89   957.8 2085.38
#Mann= 3 , 0 , 0
       0     0.1       0   470.3   0.045       0   490.3     0.1       0
Bank Sta=470.3,490.3
Exp/Cntr=0.3,0.1

Type RM Length L Ch R = 1 ,1674.4,1714.8,1674.4,1619.5
XS GIS Cut Line= 3
     2299488.242      728822.482     2299430.900      728342.333
     2299387.091      727894.567
#Sta/Elev= 30
       0 2018.14    32.2 2023.36    64.5 2026.11    96.7 2024.79   129.0 2019.42
   161.2 2011.27   193.4 2001.72   225.7 1991.27   257.9 1978.94   290.1 1966.22
   322.4 1956.88   386.8 1940.92   419.1 1935.77   441.3 1934.34   451.3 1933.70
   461.3 1933.93   483.6 1934.43   515.7 1939.44   547.8 1950.18   580.0 1964.87
   612.1 1980.19   644.2 1994.54   708.5 2022.04   740.6 2035.08   772.8 2046.96
   804.9 2057.57   837.1 2066.98   869.2 2074.64   901.3 2080.40   933.5 2083.96
#Mann= 3 , 0 , 0
       0     0.1       0   441.3   0.045       0   461.3     0.1       0
Bank Sta=441.3,461.3
Exp/Cntr=0.3,0.1