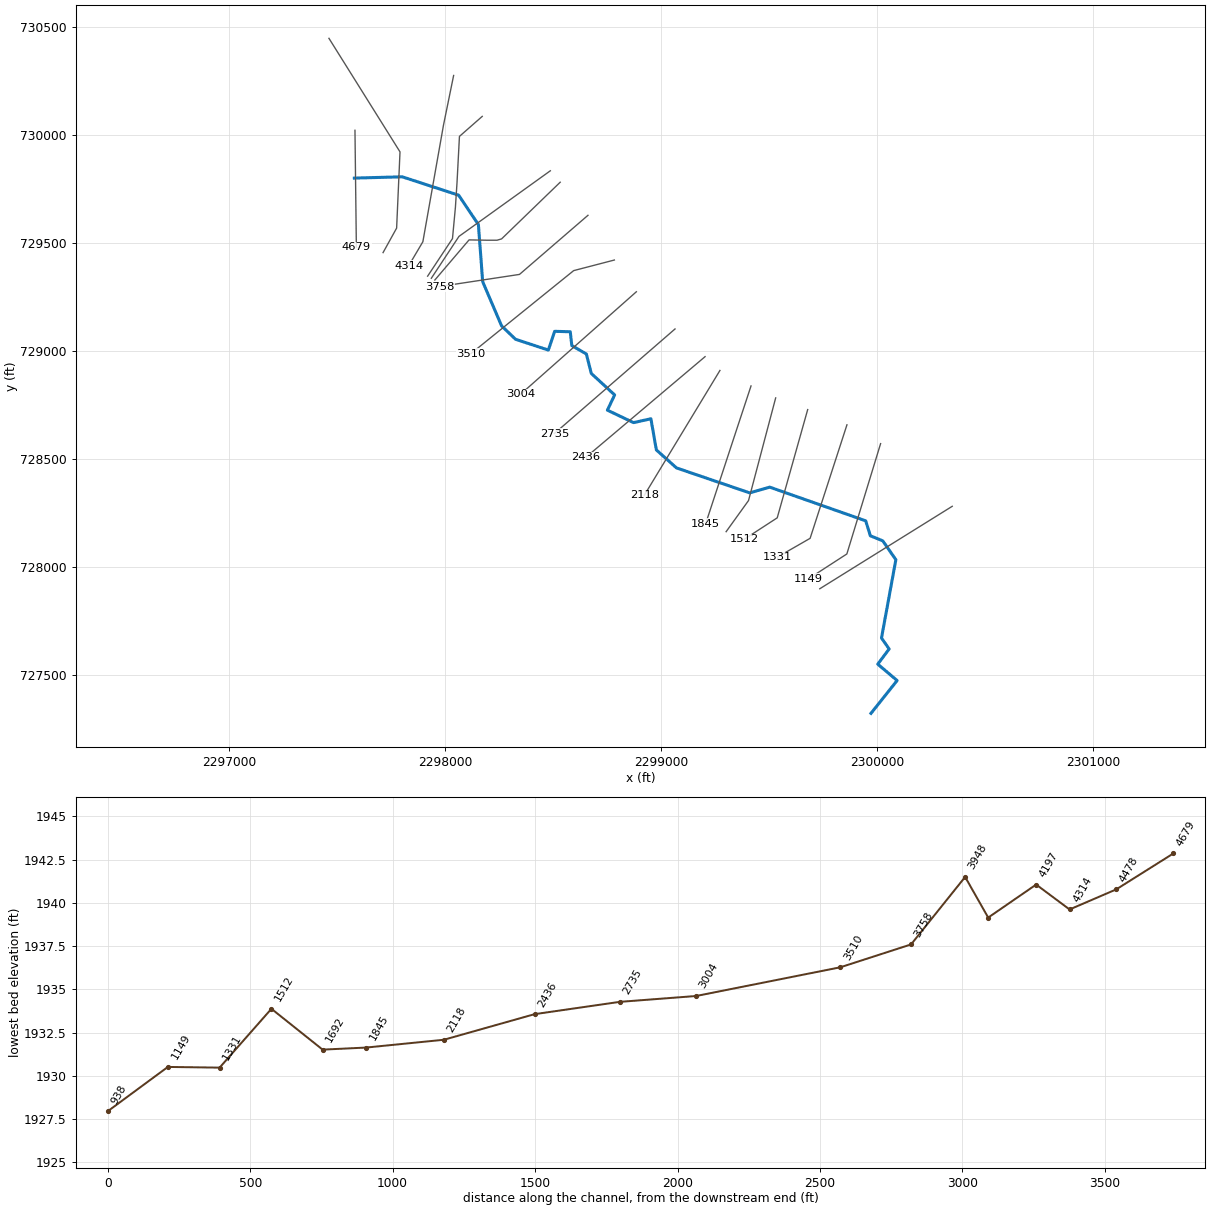
--- HORSERN.prj (project) ---

Proj Title=HORSERN
Current Plan=p01
Default Exp/Contr=0,0
English Units
Geom File=g01
Flow File=f01
Plan File=p01
BEGIN DESCRIPTION:
----------MODEL BY WOOD PLC 2022----------
AFH study
Randolph County, WV
HEC-RAS Version: RAS 6.2
Vertical Datum: NAVD88
Projection: NAD 1983 StatePlane West Virginia S FIPS 4702 (US Feet)
Terrain: 1-meter LIDAR (FEMA Region III 3DEP collected 2016-2018)
Land Use: 2019 NLCD
Hydrologic Method:
WV SIR2010-5033 regression equations
Additional Model Notes:
XS do not extend to end of reach (to tie-in) as it (and the large structure) is influenced by the mainstem. Mapping it fully caused a large backwater from the structure, so the area DS of the structure is influenced almost solely by the mainstem.
END DESCRIPTION:
DSS Export Rating Curves= 0
DSS Export Rating Curve Sorted= 0
DSS Export Volume Flow Curves= 0
DXF OffsetX= 0
DXF OffsetY= 0
DXF ScaleX= 0
DXF ScaleY= 0

--- HORSERN.p01 (plan) ---

Plan Title=Floodplain
Program Version=6.20
Short Identifier=Floodplain
Geom File=g01
Flow File=f01
Subcritical Flow
K Sum by GR= 0
Std Step Tol= 0.01
Critical Tol= 0.01
Num of Std Step Trials= 20
Max Error Tol= 0.3
Flow Tol Ratio= 0.001
Split Flow NTrial= 30
Split Flow Tol= 0.02
Split Flow Ratio= 0.02
Log Output Level= 0
Friction Slope Method= 1
Unsteady Friction Slope Method= 2
Unsteady Bridges Friction Slope Method= 1
Parabolic Critical Depth
Global Vel Dist= 0 , 0 , 0
Global Log Level= 0
CheckData=True
Encroach Param=-1 ,0,0, 0
Mapping Interval=1HOUR
Computation Time Step Use Courant=        0
Computation Time Step Use Time Series=    0
Computation Time Step Count To Double=0
Computation Time Step Max Doubling=0
Computation Time Step Max Halving=0
Computation Time Step Residence Courant=0
Run HTab= 0
Run UNet= 0
Run Sediment= 0
Run PostProcess= 0
Run WQNet= 0
Run RASMapper= 0
UNET Theta= 0
UNET Theta Warmup= 0
UNET ZTol= 0
UNET ZSATol= 0
UNET MxIter= 0
UNET Max Iter WO Improvement= 0
UNET MaxInSteps= 0
UNET DtIC= 0
UNET DtMin= 0
UNET MaxCRTS= 0
UNET WFStab= 0
UNET SFStab= 0
UNET WFX= 1
UNET SFX= 1
UNET Gravity=32.174
UNET 1D Methodology=Finite Difference
UNET DSS MLevel= 1
UNET Pardiso=0
UNET DZMax Abort= 0
UNET Use Existing IB Tables= 0
UNET Froude Reduction=False
UNET Froude Limit= 0
UNET Froude Power= 0
UNET D1 Cores= 0
UNET WindReference=Eulerian
UNET WindDragFormulation=Hsu (1988)
UNET D2 Coriolis=0
UNET D2 Cores= 0
UNET D2 Theta= 1
UNET D2 Theta Warmup= 1
UNET D2 Z Tol= 0.01
UNET D2 Volume Tol= 0.01
UNET D2 Max Iterations= 20
UNET D2 Equation= 0
UNET D2 RampUpFraction=0.1
UNET D2 TimeSlices= 1
UNET D2 Turbulence Formulation=Non-Conservative (original)
UNET D2 Eddy Viscosity=0.3
UNET D2 Transverse Eddy Viscosity=0.1
UNET D2 Smagorinsky Mixing=0
UNET D2 BCVolumeCheck=0
UNET D2 Cores=0
UNET D2 SolverType=PARDISO (Direct)
UNET D2 Minimum Iterations= 2147483647
UNET D2 Maximum Iterations= 2147483647
UNET D2 Restart Number= 10
UNET D2 Relaxation Coeff=1.3
UNET D2 SOR Precondition Iterations= 10
UNET D2 ILUT Maximum Fill= 8
UNET D2 ILUT Tolerance=1E-08
UNET D1D2 MaxIter= 0
UNET D1D2 ZTol=0.01
UNET D1D2 QTol=0.1
UNET D1D2 MinQTol=1
Write IC File= 0
Write IC File at Fixed DateTime=0
Write IC File at Sim End=0
Echo Input=False
Echo Parameters=False
Echo Output=False
Write Detailed= 0
HDF Write Warmup=0
HDF Write Time Slices=0
HDF Flush=0
HDF Compression= 1
HDF Chunk Size= 1
HDF Spatial Parts= 1
HDF Use Max Rows=0
HDF Fixed Rows= 1
Calibration Method= 0
Calibration Iterations= 20
Calibration Max Change=0.05
Calibration Tolerance=0.2
Calibration Maximum=1.5
Calibration Minimum=0.5
Calibration Optimization Method= 1
WQ AD Non Conservative
WQ ULTIMATE=-1
WQ Max Comp Step=1HOUR
WQ Output Interval=15MIN
WQ Output Selected Increments= 0
WQ Output face flow=0
WQ Output face velocity=0
WQ Output face area=0
WQ Output face dispersion=0
WQ Output cell volume=0
WQ Output cell surface area=0
WQ Output cell continuity=0
WQ Output cumulative cell continuity=0
WQ Output face conc=0
WQ Output face dconc_dx=0
WQ Output face courant=0
WQ Output face peclet=0
WQ Output face adv mass=0
WQ Output face disp mass=0
WQ Output cell mass=0
WQ Output cell source sink temp=0
WQ Output nsm pathways=0
WQ Output nsm derived pathways=0
WQ Create Restart=0
WQ Fixed Restart=0
WQ System Summary=0
WQ Write To DSS=0
Sorting and Armoring Iterations= 10
XS Update Threshold= 0.02
Bed Roughness Predictor= 0
Hydraulics Update Threshold= 0.02
Energy Slope Method= 1
Volume Change Method= 1
Sediment Retention Method= 0
Sediment TS Multiplier= 1
Warm Up Method= 0
XS Weighting Method= 0
Number of US Weighted Cross Sections= 1
Number of DS Weighted Cross Sections= 1
Upstream XS Weight=0
Main XS Weight=1
Downstream XS Weight=0
Number of DS XS's Weighted with US Boundary= 1
Upstream Boundary Weight= 1
Weight of XSs Associated with US Boundary= 0
Number of US XS's Weighted with DS Boundary= 1
Downstream Boundary Weight= 0.5
Weight of XSs Associated with DS Boundary= 0.5
Percentile Method= 0
Sediment Output Level= 3
Mass or Volume Output= 0
Output Increment Type= 1
Profile and TS Output Increment= 1
Transport Output Increment 1
XS Output Flag= 0
XS Output Increment= 10
Read HDF5 Sediment Hotstart= 0
Sediment Hotstart Type= 0
Write Gradation File= 0
Read Gradation Hotstart= 0
Write HDF5 File= 1
Write Binary Output= 1
Write DSS Sediment File= 0
DSS Sediment Output Type= 1
SV Curve= 0
Specific Gage Flag= 0
Subcell Erosion Methods= 0
Subcell Deposition Methods= 0
Advection Scheme= 1
Matrix Solver= 0
Implicit Weighting Factor= 1
Maximum Outer Loop Convergence Iterations= 5
Convergence Maximum Absolute= 0.001
Convergence RMSE= 0.0001
Grain Fractions Max Abs Error= 0.001
Max Subgrid Regions= 1
Max Subgrid Length Scale= 3.402823E+38
Initial Layer Thickness= 3.402823E+38
Min Layer Thickness= 3.402823E+38
Max Layer Thickness= 3.402823E+38
Number of Layers= 5

--- HORSERN.f01 (steady flow) ---

Flow Title=Flow
Program Version=4.00
Number of Profiles=1
Profile Names=P100yr
River Rch & RM=HORSERN,Main,4679
     371
Boundary for River Rch & Prof#=HORSERN,Main      ,1
Up Type=0
Dn Type=3
Dn Slope=0.002042

--- HORSERN.g01 (geometry) ---

Geom Title=Geometry
Program Version=6.20

River Reach=HORSERN         ,Main
Reach XY= 30
     2297579.967      729801.367     2297801.495       729807.27
     2298062.606        729722.2     2298153.926      729586.089
     2298173.718      729322.201     2298261.217      729117.339
     2298325.801      729055.534     2298477.537      729005.534
     2298506.935      729092.339     2298579.157      729090.256
     2298586.102      729026.367     2298653.463      728987.478
      2298676.38        728897.2       2298784.4      728797.964
     2298750.807      728727.391     2298871.889      728669.785
     2298952.184       728687.58     2298977.358      728543.483
     2299070.674       728460.15     2299409.216      728344.698
     2299502.098      728371.174     2299946.108      728215.358
     2299967.809      728145.9142300025.17903984728122.777503905
     2300085.749      728035.381       2300019.3      727672.925
     2300054.716       727622.23     2300001.939      727552.091
     2300091.522      727476.397     2299970.593      727324.284

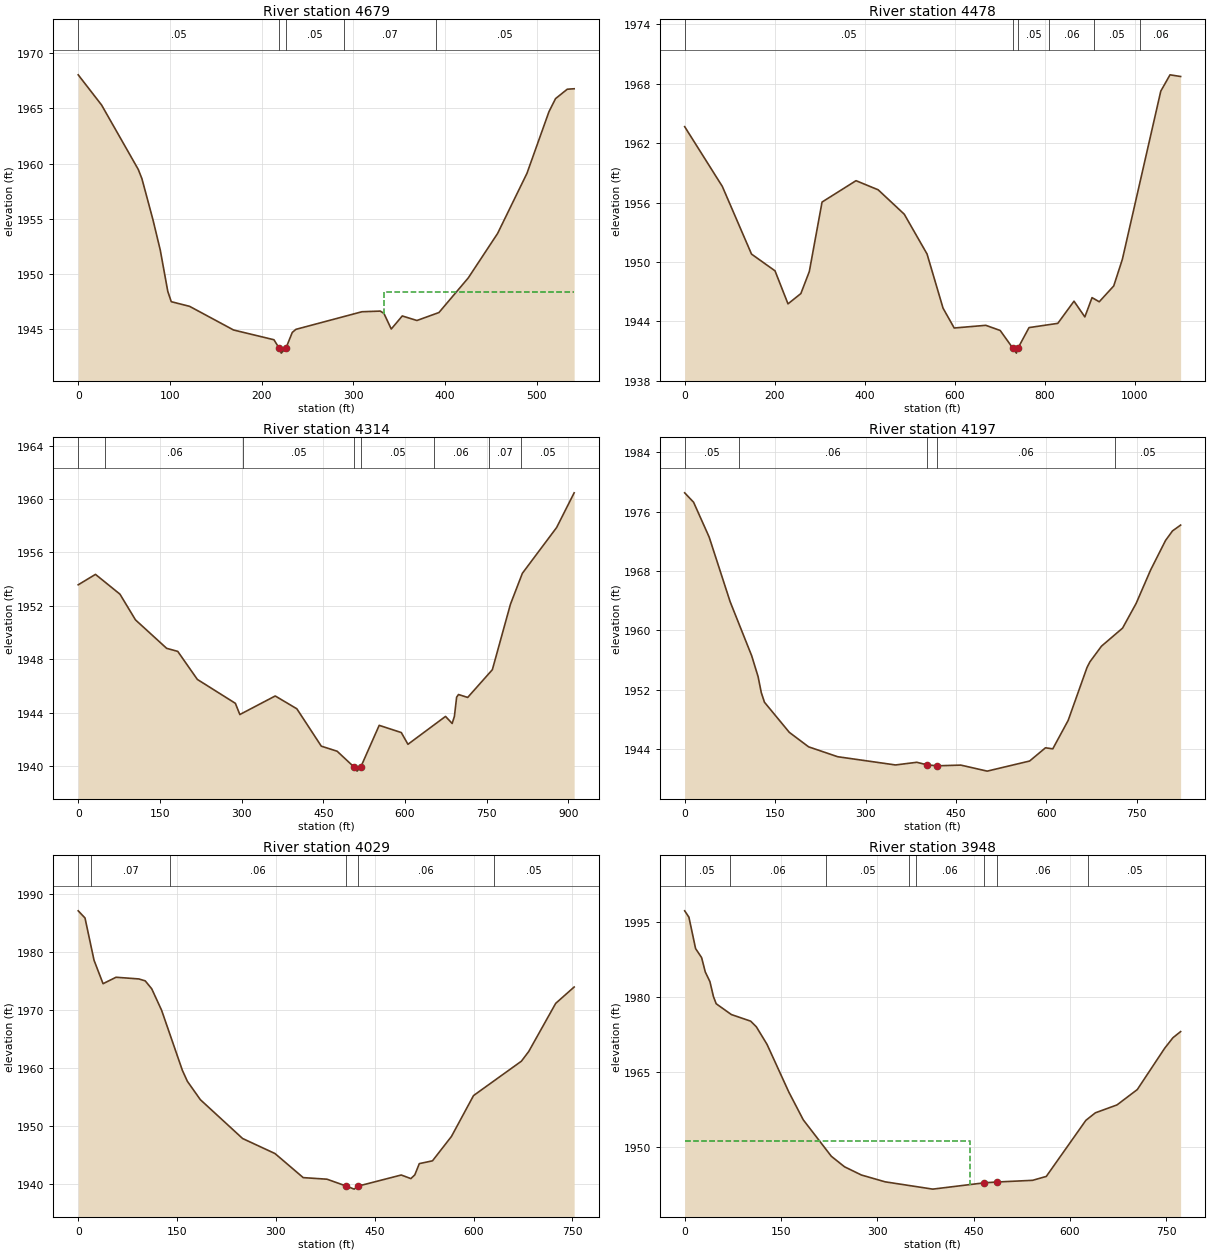
Type RM Length L Ch R = 1 ,4679    ,200.9,200.9,200.9
XS GIS Cut Line= 2
2297582.72286292730022.6368464432297589.18884251729481.700265908
#Sta/Elev= 30
       0 1968.02    25.5 1965.29    65.5 1959.47    69.5 1958.63    81.5 1954.93
    89.5 1952.18    97.7 1948.45   101.5 1947.51   121.5 1947.09   169.5 1944.95
   213.5 1944.07  219.22 1943.31   221.5 1942.86   226.7 1943.33   233.5 1944.73
   237.5 1945.01   309.5  1946.6   329.5 1946.66   333.5 1946.45   341.5 1945.04
   353.5 1946.22   369.5 1945.81   393.5 1946.53   425.5 1949.66   457.5 1953.68
   489.5 1959.11   513.5 1964.68   520.7 1965.87   533.5 1966.72     541 1966.76
#Mann= 5 ,-1,0
       0     .05       0  219.22    .045       0   226.7     .05       0
     290     .07       0     390     .05       0
#XS Ineff= 2 , 0
                          334.01         1948.38
Permanent Ineff=
       F       F
Bank Sta=219.22,226.7
XS Rating Curve= 0 ,0
Exp/Cntr(USF)=0,0
Exp/Cntr=0.3,0.1

Type RM Length L Ch R = 1 ,4478    ,163.7,163.7,163.7
XS GIS Cut Line= 4
2297462.34042457730448.1098947482297791.12593782729922.685766478
2297775.48213713729569.9150568972297712.76065146  729456.5460426
#Sta/Elev= 30
       0 1963.67    83.7 1957.63   148.6 1950.79   200.8  1949.1   229.7 1945.76
   258.3  1946.8   277.1 1949.03   305.4 1956.05   380.9 1958.21   430.1 1957.29
   488.2 1954.82   538.8  1950.8   574.4 1945.32   599.2 1943.32   669.4 1943.59
   701.4 1943.07729.80521941.263   737.4 1940.78  740.76 1941.27   765.5 1943.36
   829.5 1943.79   865.5 1946.03   889.6 1944.44   905.6 1946.39   921.6 1945.97
   953.8 1947.57     973 1950.26  1058.4 1967.26  1078.9 1968.91  1102.5 1968.74
#Mann= 6 ,-1,0
       0     .05       0729.8052    .045       0  740.76     .05       0
  809.81     .06       0  909.81     .05       0 1012.93     .06       0
Bank Sta=729.8052,740.76
XS Rating Curve= 0 ,0
Exp/Cntr(USF)=0,0
Exp/Cntr=0.3,0.1

Type RM Length L Ch R = 1 ,4314    ,117.3,117.3,117.3
XS GIS Cut Line= 4
2298039.27900544730276.2624128692297992.55484035 730047.50184336
2297896.94298586729506.7649225542297831.79258175729396.529878754
#Sta/Elev= 30
       0 1953.58    31.7 1954.36    76.6 1952.88   105.2 1950.95   162.4 1948.82
   182.8 1948.59   218.8 1946.49   288.6  1944.7   296.8 1943.86   361.8 1945.25
   401.5 1944.29   446.4 1941.49   475.5 1941.11506.66481939.922   512.1 1939.62
   518.9 1939.93   552.7 1943.05   593.3 1942.51   605.5 1941.63   674.5 1943.72
   686.7 1943.19   690.8 1943.72   694.9 1945.16   698.3 1945.36   715.2 1945.14
   760.5 1947.22   793.7 1952.12   815.6 1954.44   878.5 1957.87   910.7 1960.47
#Mann= 8 ,-1,0
       0      .1       0      50     .06       0  303.48     .05       0
506.6648    .045       0   518.9     .05       0  653.48     .06       0
  753.48     .07       0  812.61     .05       0
Bank Sta=506.6648,518.9
XS Rating Curve= 0 ,0
Exp/Cntr(USF)=0,0
Exp/Cntr=0.3,0.1

Type RM Length L Ch R = 1 ,4197    ,168.4,168.4,168.4
BEGIN DESCRIPTION:
Structure
END DESCRIPTION:
XS GIS Cut Line= 6
2298171.70492648730086.9514606012298066.19322048729994.318568816
2298055.02992689729781.6555689222298047.50829864729665.822493975
 2298033.9693678729521.4072317032297919.00880173729347.642576026
#Sta/Elev= 30
       0 1978.52    14.8 1977.25    40.6 1972.57    75.4 1963.87   111.2 1956.58
   121.8 1953.78   127.1 1951.63   132.4 1950.33   173.6 1946.28   205.6 1944.33
   253.8    1943   349.8 1941.89   385.1 1942.25   402.3  1941.9 418.5481941.776
   458.1 1941.87   501.9 1941.06   572.3 1942.42   598.6  1944.2   610.7 1944.06
   636.2 1947.88   667.5 1955.01   672.3 1955.77   691.5 1957.88   726.5 1960.31
   749.1 1963.65     773 1968.13   797.8 1972.11   809.3 1973.39   822.8 1974.18
#Mann= 5 ,-1,0
       0     .05       0      90     .06       0   402.3    .045       0
 418.548     .06       0  714.49     .05       0
Bank Sta=402.3,418.548
XS Rating Curve= 0 ,0
Exp/Cntr(USF)=0,0
Exp/Cntr=0.3,0.1

Type RM Length L Ch R = 1 ,4029    ,80.9,80.9,80.9
XS GIS Cut Line= 3
2298486.79414059729835.1868061842298064.03185422 729531.57982495
 2297936.0889578729337.837724659
#Sta/Elev= 30
       0 1987.04    10.3 1985.81      24 1978.54    37.7  1974.5    57.4 1975.61
    91.9 1975.32   101.7 1974.99   111.6 1973.62   126.6 1969.92   158.1 1959.59
   165.7  1957.7   185.4 1954.54   249.5 1947.86   298.7 1945.27   341.5 1941.13
   377.5 1940.86406.51921939.692   418.9 1939.15424.21881939.649   490.3 1941.58
   504.9 1940.96   510.9 1941.61   517.7 1943.54   537.7 1944.02   566.5 1948.22
     600 1955.25   672.7 1961.17   683.8 1962.84   724.7 1971.12   752.7 1973.93
#Mann= 6 ,-1,0
       0     .05       0      20     .07       0     140     .06       0
406.5192    .045       0424.2188     .06       0  630.49     .05       0
Bank Sta=406.5192,424.2188
XS Rating Curve= 0 ,0
Exp/Cntr(USF)=0,0
Exp/Cntr=0.3,0.1

Type RM Length L Ch R = 1 ,3948    ,189.9,189.9,189.9
BEGIN DESCRIPTION:
Structure
END DESCRIPTION:
XS GIS Cut Line= 6
   2298532.42738729782.3000023042298261.12254075729519.902906054
2298240.06198167 729513.885603462298191.92356092 729513.88560346
2298110.68997589729515.3899291082297952.38978788 729329.72605755
#Sta/Elev= 30
       0 1997.15     6.6 1995.88      17  1989.6    26.4 1987.79    32.1 1984.93
    39.3    1983    44.9 1979.97    49.1 1978.57    72.7 1976.41   102.8 1975.09
   111.6 1973.97   128.3 1970.45   162.2 1960.93   184.8 1955.35   228.5 1948.07
     249 1945.97   275.4 1944.32   312.3 1942.96   386.5  1941.5 466.9961942.765
 486.9961942.926   542.1 1943.26   563.4 1944.04   625.1 1955.26   639.9 1956.76
   673.6 1958.34   705.2 1961.41   747.7 1969.64   760.7 1971.77   772.7    1973
#Mann= 8 ,-1,0
       0     .05       0      70     .06       0     220     .05       0
     350     .07       0     360     .06       0 466.996    .045       0
 486.996     .06       0  628.73     .05       0
#XS Ineff= 2 , 0
          444.77 1951.07
Permanent Ineff=
       F       F
Bank Sta=466.996,486.996
XS Rating Curve= 0 ,0
Exp/Cntr(USF)=0,0
Exp/Cntr=0.3,0.1

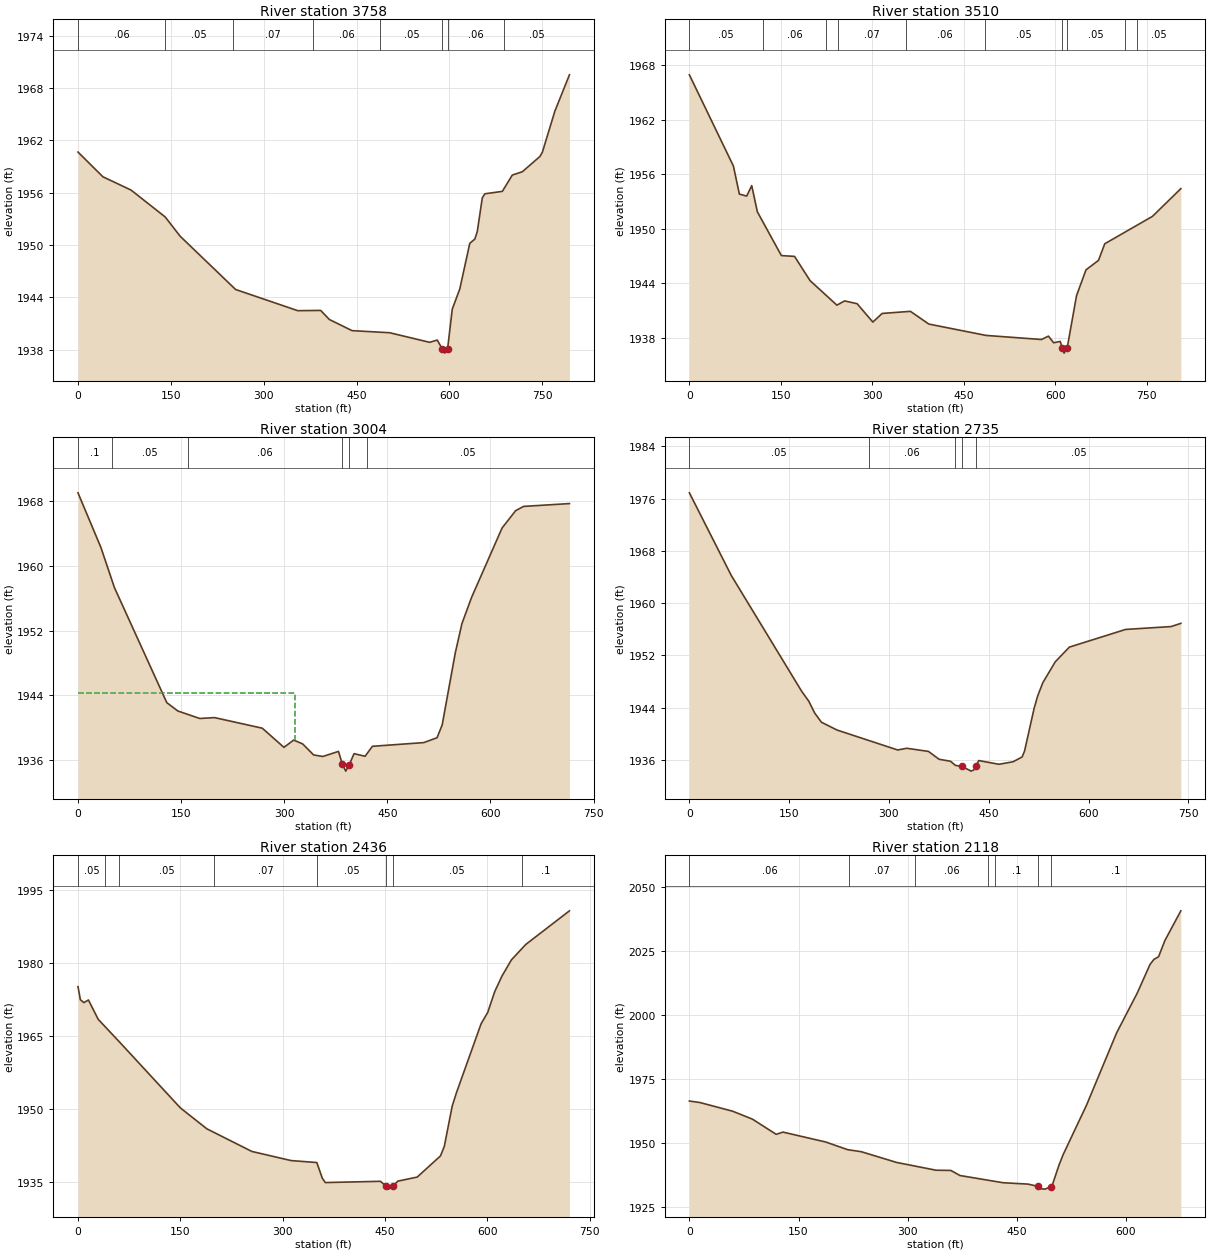
Type RM Length L Ch R = 1 ,3758    ,247.9,247.9,247.9
XS GIS Cut Line= 3
2298661.00364374729629.184025527 2298344.0329698 729355.62269112
2297972.98701033729299.355691828
#Sta/Elev= 30
       0 1960.67    40.3 1957.83    85.7 1956.31   140.8 1953.23   165.1 1951.01
   254.7  1944.9   355.1 1942.47   392.1  1942.5   406.1 1941.46   442.8 1940.18
   503.5 1939.94   568.2 1938.84   580.4  1939.1   588.5 1938.09   592.5  1937.6
  597.14  1938.1   604.7 1942.65   616.8 1944.95     633  1950.2   641.1 1950.68
   645.1 1951.54   653.2 1955.41   657.3 1955.88   685.6 1956.16   701.7 1958.03
   717.9 1958.41   746.3 1960.16   750.3 1960.66   770.5 1965.37     794 1969.53
#Mann= 8 ,-1,0
       0     .06       0     140     .05       0     250     .07       0
     380     .06       0   488.7     .05       0   588.5    .045       0
  597.14     .06       0   688.7     .05       0
Bank Sta=588.5,597.14
XS Rating Curve= 0 ,0
Exp/Cntr(USF)=0,0
Exp/Cntr=0.3,0.1

Type RM Length L Ch R = 1 ,3510    ,506.3,506.3,506.3
XS GIS Cut Line= 3
2298783.14775243729422.2348742562298594.84102386729373.204728218
2298119.13501527728988.841275851
#Sta/Elev= 30
       0 1966.92    72.2 1956.88      82 1953.79      94 1953.57   102.3 1954.72
   111.5 1951.84   150.9 1947.02   172.5 1946.93     198 1944.26     242 1941.56
   254.6 1942.03   275.2 1941.72   300.9  1939.7   316.3 1940.65   362.6 1940.88
   392.8 1939.48   486.6 1938.23   577.6 1937.78     589 1938.15   597.6 1937.42
   608.3 1937.57  612.06 1936.82   614.7 1936.28   619.7 1936.83   635.1 1942.61
   650.6 1945.45   671.1 1946.49   681.4 1948.32   759.7 1951.34   806.2 1954.39
#Mann= 10 ,-1,0
       0     .05       0     120     .06       0  224.59     .05       0
  244.59     .07       0  354.59     .06       0  484.59     .05       0
  612.06    .045       0   619.7     .05       0  714.59      .1       0
  734.59     .05       0
Bank Sta=612.06,619.7
XS Rating Curve= 0 ,0
Exp/Cntr(USF)=0,0
Exp/Cntr=0.3,0.1

Type RM Length L Ch R = 1 ,3004    ,268.7,268.7,268.7
XS GIS Cut Line= 2
2298884.90127794729275.3241585082298349.60488476 728801.52605112
#Sta/Elev= 30
       0 1969.04    33.4 1962.27      53 1957.32   129.2 1943.09   145.2 1942.06
   177.2 1941.13   198.6 1941.24   268.1 1939.93   299.6 1937.56   313.7 1938.46
   326.8 1937.99   342.8 1936.62   356.2 1936.43   378.9 1937.06   384.6 1935.48
   389.5 1934.62  394.66 1935.43   401.6 1936.78   417.6 1936.46   428.3 1937.69
   503.1 1938.15   522.3 1938.75   529.8 1940.34   548.9 1949.27   558.5 1952.86
   572.5  1956.1   616.9 1964.69   636.6 1966.83   648.1 1967.36   714.9 1967.71
#Mann= 6 ,-1,0
       0      .1       0      50     .05       0     160     .06       0
   384.6    .045       0  394.66     .06       0     420     .05       0
#XS Ineff= 2 , 0
          315.96 1944.34
Permanent Ineff=
       F       F
Bank Sta=384.6,394.66
XS Rating Curve= 0 ,0
Exp/Cntr(USF)=0,0
Exp/Cntr=0.3,0.1

Type RM Length L Ch R = 1 ,2735    ,298.5,298.5,298.5
XS GIS Cut Line= 2
2299063.79404532729103.1798949462298505.49977192728619.326178489
#Sta/Elev= 30
       0  1976.9      63 1964.24   168.9 1946.49   179.5 1944.99   188.3 1943.19
   198.5 1941.77   221.8 1940.58   313.1 1937.52   326.8 1937.78   359.4  1937.3
   375.3  1936.1   392.5 1935.79     400 1935.16   409.5    1935   423.7 1934.28
   428.2 1934.51  430.57 1935.06     435  1935.9   465.3 1935.33   486.5 1935.71
   500.2 1936.45   503.9 1937.37   518.2 1943.88   523.5 1945.77   531.4 1947.84
     550 1951.02   571.2 1953.27   655.8 1955.98   724.2 1956.42   738.8 1956.91
#Mann= 5 ,-1,0
       0     .05       0     270     .06       0     400     .05       0
   409.5    .045       0  430.57     .05       0
Bank Sta=409.5,430.57
XS Rating Curve= 0 ,0
Exp/Cntr(USF)=0,0
Exp/Cntr=0.3,0.1

Type RM Length L Ch R = 1 ,2436    ,318.7,318.7,318.7
XS GIS Cut Line= 2
2299202.85668759 728975.034221072298652.63405892728510.345398827
#Sta/Elev= 30
       0 1975.21     3.5 1972.53     8.7 1971.93    15.3 1972.47    29.7 1968.48
      60 1963.96   150.1 1950.27   188.9 1945.97   254.8 1941.32   312.4 1939.44
     350 1939.04     358 1935.84   362.4 1934.92   443.3 1935.18451.60491934.133
   455.4 1933.57461.60471934.191   468.7 1935.21   497.1 1936.05   531.2  1940.4
   536.8 1942.35   548.4 1950.65   554.6 1953.39   590.8  1967.6   600.4  1969.9
   610.8 1974.23   621.3 1977.38   635.2 1980.73   656.1 1983.88   720.2 1990.81
#Mann= 8 ,-1,0
       0     .05       0      40     .06       0      60     .05       0
     200     .07       0     350     .05       0451.6049    .045       0
461.6047     .05       0     650      .1       0
Bank Sta=451.6049,461.6047
XS Rating Curve= 0 ,0
Exp/Cntr(USF)=0,0
Exp/Cntr=0.3,0.1

Type RM Length L Ch R = 1 ,2118    ,272.4,272.4,272.4
XS GIS Cut Line= 2
2299271.61409332728911.2065290552298921.67987642728333.651173044
#Sta/Elev= 30
       0 1966.46    14.4 1965.88    59.3  1962.5    86.6  1959.4   119.3 1953.46
   128.6 1954.34   187.5 1950.46   217.5 1947.48   236.2 1946.69   284.5 1942.52
   338.9 1939.47   359.3 1939.38   371.8  1937.4   431.2 1934.58   465.4 1934.05
   479.4 1933.13   484.5 1932.18   488.8 1932.09  496.99 1933.09   499.1 1934.04
   507.8 1941.41   513.6 1945.57   545.7 1964.85     587 1993.02   615.6  2008.7
     633 2019.79   638.4 2021.73   644.7 2022.77   653.4 2029.09   675.3 2040.67
#Mann= 7 ,-1,0
       0     .06       0     220     .07       0     310     .06       0
     410     .05       0     420      .1       0   479.4    .045       0
  496.99      .1       0
Bank Sta=479.4,496.99
XS Rating Curve= 0 ,0
Exp/Cntr(USF)=0,0
Exp/Cntr=0.3,0.1

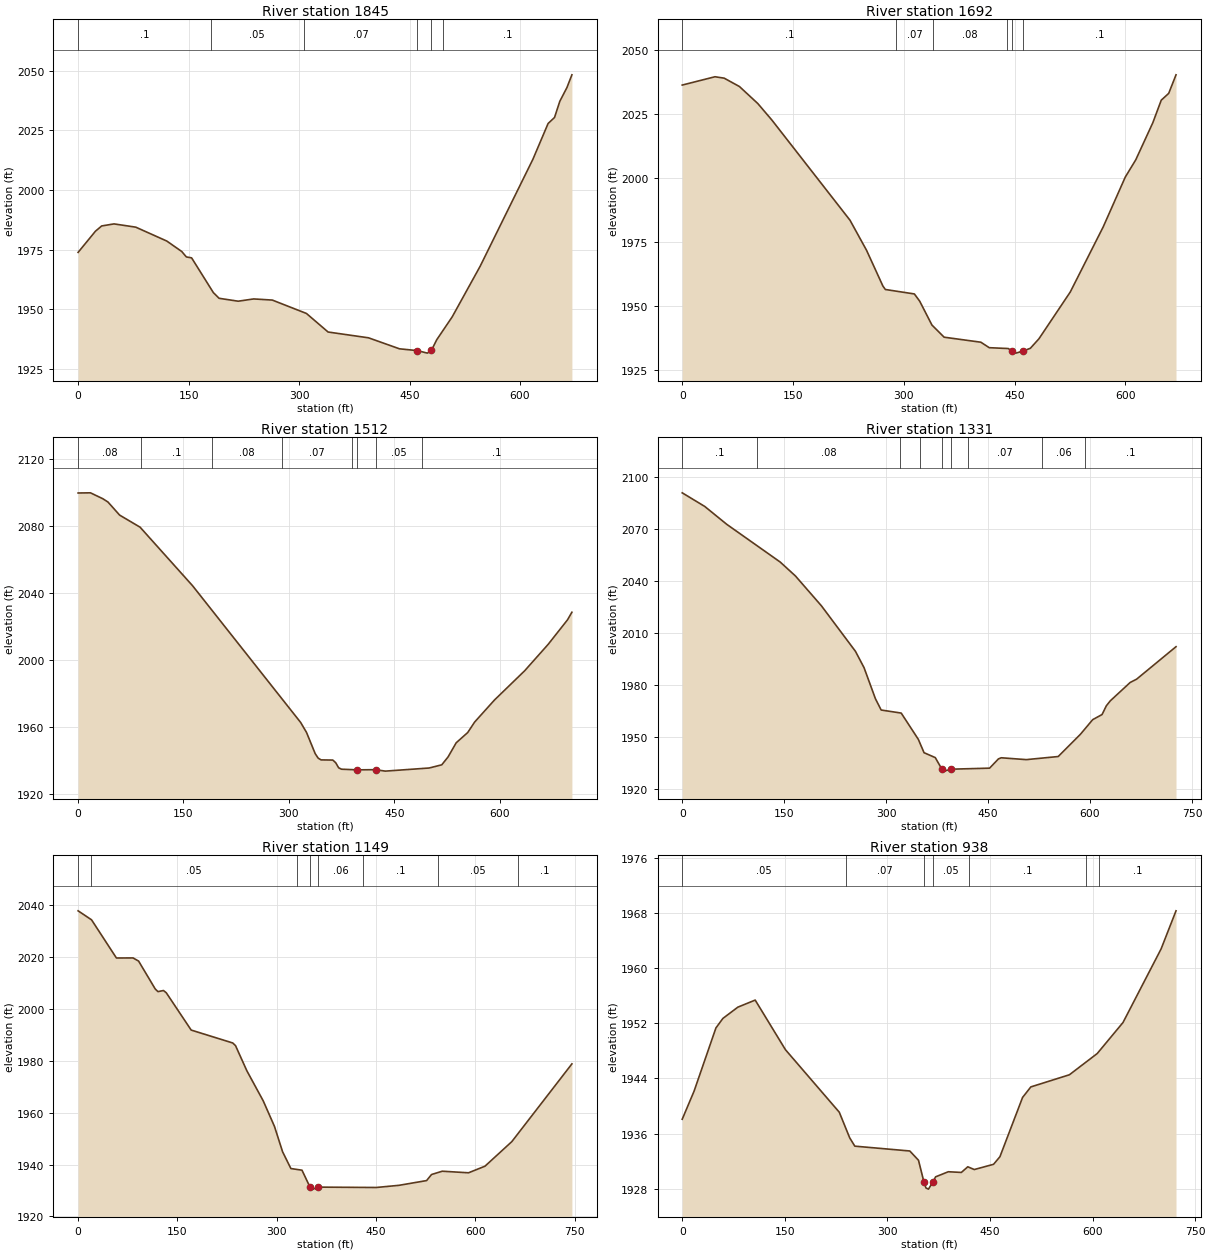
Type RM Length L Ch R = 1 ,1845    ,153.1,153.1,153.1
XS GIS Cut Line= 3
2299415.52597596728839.5490531152299350.90765341728643.930501393
2299205.82040887728202.746839427
#Sta/Elev= 30
       0 1973.88    23.6 1982.77      32 1984.96    48.8 1985.82    78.3 1984.45
   120.4 1978.63   140.7 1974.25     147 1971.97   154.1 1971.58   183.6 1957.03
   191.4 1954.63   217.3 1953.41   238.4 1954.36   263.7 1953.88     310 1948.27
   339.4 1940.49   394.3 1938.06   436.3 1933.45   460.7 1932.69   474.2 1931.64
479.67581932.768   486.8  1937.2   507.9 1946.85   545.8 1968.04   617.4 2012.88
   638.1 2027.92   646.8 2030.43     654 2037.23   663.7 2043.01   670.4 2048.32
#Mann= 6 ,-1,0
       0      .1       0     180     .05       0  306.01     .07       0
   460.7    .045       0479.6758     .07       0  496.01      .1       0
Bank Sta=460.7,479.6758
XS Rating Curve= 0 ,0
Exp/Cntr(USF)=0,0
Exp/Cntr=0.3,0.1

Type RM Length L Ch R = 1 ,1692    ,179.7,179.7,179.7
XS GIS Cut Line= 3
2299529.56521063728784.1030844482299403.98567787 728309.23188436
2299300.35193177728165.131627879
#Sta/Elev= 30
       0 2036.16    44.4 2039.41    56.8 2038.86    77.5 2035.59   102.3 2028.97
   121.3 2022.55   227.2 1983.41   249.7 1971.62   271.8 1957.69   275.1 1956.36
   314.4 1954.62   321.6  1951.8   338.2 1942.47   354.7 1937.74   404.4 1935.78
   415.8 1933.64   441.6 1933.31446.53651932.292   451.8 1931.52461.63651932.323
   471.5 1933.43     483 1937.09   525.5 1955.38   570.1  1980.8     600 2000.25
   614.2 2006.99   637.3 2021.46   648.7 2030.26   658.8 2032.92   668.7 2040.16
#Mann= 6 ,-1,0
       0      .1       0     290     .07       0     340     .08       0
     440      .1       0446.5365    .045       0461.6365      .1       0
Bank Sta=446.5365,461.6365
XS Rating Curve= 0 ,0
Exp/Cntr(USF)=0,0
Exp/Cntr=0.3,0.1

Type RM Length L Ch R = 1 ,1512    ,181.9,181.9,181.9
BEGIN DESCRIPTION:
Structure
END DESCRIPTION:
XS GIS Cut Line= 3
2299677.71905044728730.0825819292299536.79069082728229.191499501
 2299383.8046836728129.708037434
#Sta/Elev= 30
       0  2099.8    17.6  2099.9    35.2 2096.37    42.5 2094.41    59.1 2086.61
    88.2 2079.41     163 2044.43   316.7 1962.94   325.1 1956.96   337.5 1944.26
   341.7 1941.62   345.8 1940.58   362.5 1940.48   366.6 1938.91   370.8 1935.88
   374.9 1935.03397.11151934.644   423.6 1934.74   437.2 1933.88   499.6 1935.74
   517.6 1937.65   526.6 1942.38   538.1 1950.77   554.5  1956.9   564.4 1963.17
   592.6  1976.3   635.6 1993.76     669  2009.5   696.5 2024.11   702.8 2028.67
#Mann= 8 ,-1,0
       0     .08       0      90      .1       0     190     .08       0
     290     .07       0     390     .05       0397.1115    .045       0
   423.6     .05       0     490      .1       0
Bank Sta=397.1115,423.6
XS Rating Curve= 0 ,0
Exp/Cntr(USF)=0,0
Exp/Cntr=0.3,0.1

Type RM Length L Ch R = 1 ,1331    ,181.6,181.6,181.6
XS GIS Cut Line= 3
2299859.41821586728659.6199174782299688.96485857728134.342592329
2299537.83846025 728047.52339783
#Sta/Elev= 30
       0 2090.75    33.1 2082.92    65.6 2072.59   144.2 2050.88   166.6 2042.86
   204.9 2025.63   254.9 1999.46   267.5 1990.07   284.3 1972.14   292.7 1965.67
   322.2 1963.91   347.4 1948.77   355.8 1941.09   372.3 1938.27   382.3 1931.43
   385.3 1930.48     395 1931.59   452.2 1932.19   465.2 1937.51   469.4 1938.17
   506.2  1937.1   553.2 1938.89   585.9 1951.72   603.9 1960.12   617.7 1963.07
     624 1968.11   629.8 1970.96   659.1 1981.55   668.5 1983.43   726.5 2002.14
#Mann= 9 ,-1,0
       0      .1       0     110     .08       0     320     .05       0
     350     .06       0   382.3    .045       0     395     .06       0
     420     .07       0     530     .06       0  592.24      .1       0
Bank Sta=382.3,395
XS Rating Curve= 0 ,0
Exp/Cntr(USF)=0,0
Exp/Cntr=0.3,0.1

Type RM Length L Ch R = 1 ,1149    ,211,211,211
XS GIS Cut Line= 3
2300015.15345406728572.5486717922299858.94613524728061.963468069
2299681.05618819727946.801535143
#Sta/Elev= 30
       0 2037.69    20.3 2034.23    57.9 2019.52      83 2019.55    91.4 2018.33
   116.5  2007.6   120.6 2006.58     129    2007   133.2 2006.13   170.8 1991.77
   233.6  1986.8   237.8 1985.77   254.9  1976.1   279.6 1964.53   296.6 1954.68
   308.9 1944.89   321.4 1938.45   338.2 1937.81350.23711931.331   354.9 1930.52
362.83681931.291   450.3 1931.15   484.6 1931.98   526.4 1933.81   533.9 1936.15
   550.1 1937.42   589.7 1936.81   614.6 1939.35   655.1  1948.8   745.9 1978.75
#Mann= 8 ,-1,0
       0      .1       0      20     .05       0     330     .06       0
350.2371    .045       0362.8368     .06       0     430      .1       0
  543.95     .05       0  663.95      .1       0
Bank Sta=350.2371,362.8368
XS Rating Curve= 0 ,0
Exp/Cntr(USF)=0,0
Exp/Cntr=0.3,0.1

Type RM Length L Ch R = 1 ,938     ,,,
XS GIS Cut Line= 2
2300346.71530182 728282.59528852 2299733.6860524727900.959906059
#Sta/Elev= 30
       0 1938.09    17.4 1942.18    49.3 1951.33    59.5 1952.71    81.3 1954.34
   106.7 1955.37     151 1948.17   229.7 1939.11   244.9  1935.4   252.4 1934.19
   332.8 1933.49   345.5 1932.15  353.36 1929.04   356.4 1928.13   360.1 1927.96
  366.93 1929.05   370.5 1929.74   389.1 1930.48   408.2 1930.38   417.6  1931.2
   427.1  1930.8   455.3 1931.56   464.6 1932.66   497.7 1941.25   509.8 1942.78
   566.2 1944.54   606.9 1947.62   644.6 1952.12   700.3 1962.79   722.1 1968.31
#Mann= 7 ,-1,0
       0     .05       0     240     .07       0  353.36    .045       0
  366.93     .05       0     420      .1       0     590     .05       0
     610      .1       0
Bank Sta=353.36,366.93
XS Rating Curve= 0 ,0
Exp/Cntr(USF)=0,0
Exp/Cntr=0.3,0.1
LCMann Table=0

Chan Stop Cuts=-1
Use User Specified Reach Order=0
Composite Channel Slope=5